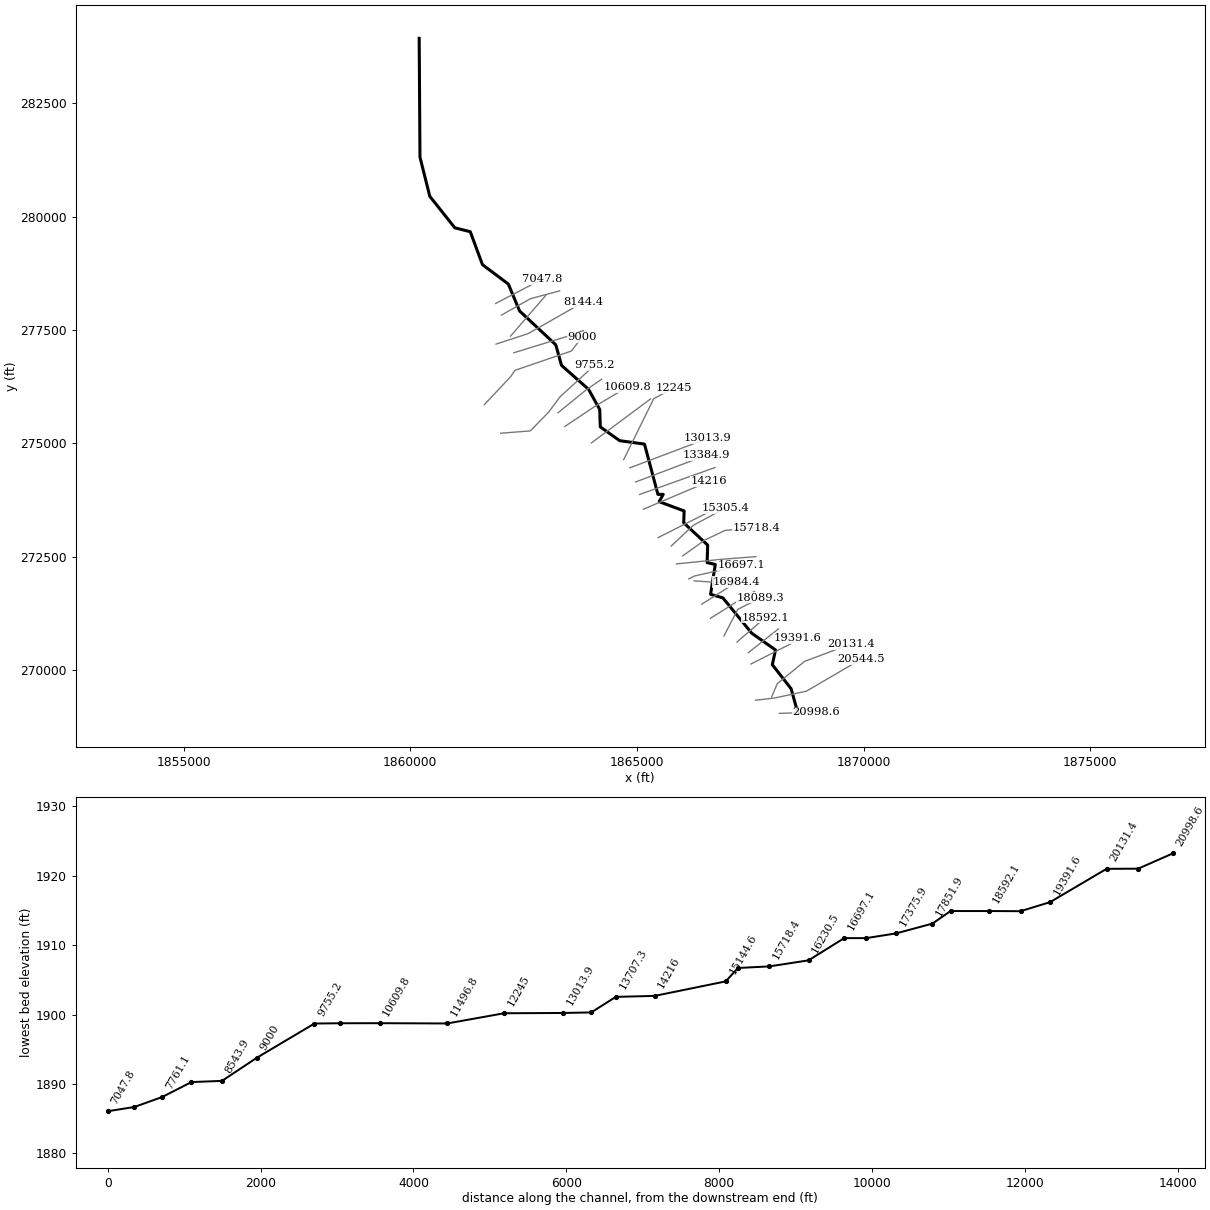
--- RckhsCrk1.prj (project) ---

Proj Title=RckhsCrk1
Current Plan=p01
Default Exp/Contr=0,0
English Units
Geom File=g01
Flow File=f01
Plan File=p01
BEGIN DESCRIPTION:
END DESCRIPTION:
DSS Export Rating Curves= 0
DSS Export Rating Curve Sorted= 0
DSS Export Volume Flow Curves= 0
DXF OffsetX= 0
DXF OffsetY= 0
DXF ScaleX= 0
DXF ScaleY= 0

--- RckhsCrk1.p01 (plan) ---

Plan Title=Floodplain
Program Version=4.00
Geom File=g01
Flow File=f01
K Sum by GR=0
Std Step Tol=0.01
Critical Tol=0.01
Num of Std Step Trials=20
Max Error Tol=0.3
Flow Tol Ratio=0.001
Split Flow NTrial=30
Split Flow Tol=0.02
Split Flow Ratio=0.02
Log Output Level=0
Friction Slope Method=1
Unsteady Friction Slope Method=2
Unsteady Bridges Friction Slope Method=1
Global Log Level=0
CheckData=False
Run HTab=0
Run UNet=0
Run PostProcess=0
UNET Theta=0
UNET Theta Warmup=0
UNET ZTol=0
UNET ZSATol=0
UNET MxIter=0
UNET MaxInSteps=0
UNET DtIC=0
UNET DtMin=0
UNET MaxCRTS=0
UNET WFStab=0
UNET SFStab=0
UNET WFX=0
UNET SFX=0
UNET DSS MLevel=0
UNET DZMax Abort=0
UNET Convert EG Bridges=0
UNET Use Existing IB Tables=0
UNET Froude Limit=0
UNET Froude Power=0
Write IC File=0
Echo Input=False
Echo Output=False
Write Detailed=0

--- RckhsCrk1.f01 (steady flow) ---

Flow Title=NFF Regression Equation
Program Version=4.10
Number of Profiles= 1
Profile Names=P100yr
River Rch & RM=RckhsCrk1,Main            ,20998.6
780.6195
River Rch & RM=RckhsCrk1,Main            ,19391.6
802.7889
River Rch & RM=RckhsCrk1,Main            ,19005.1
 1044.03
River Rch & RM=RckhsCrk1,Main            ,18089.3
1052.326
River Rch & RM=RckhsCrk1,Main            ,17375.9
1167.979
River Rch & RM=RckhsCrk1,Main            ,15305.4
1285.856
River Rch & RM=RckhsCrk1,Main            ,13707.3
1372.141
River Rch & RM=RckhsCrk1,Main            ,12245
 1509.65
River Rch & RM=RckhsCrk1,Main            ,8543.9
1580.699
River Rch & RM=RckhsCrk1,Main            ,8144.4
2335.989
River Rch & RM=RckhsCrk1,Main            ,7047.8
2386.395
River Rch & RM=RckhsCrk1,Main            ,582.8
2645.318
Boundary for River Rch & Prof#=RckhsCrk1,Main            , 1
Up Type= 0
Dn Type= 3
Dn Slope=0.0035
DSS Import GetInterval= 0
DSS Import GetPeak= 0
DSS Import FillOption= 0

--- RckhsCrk1.g01 (geometry) ---

Geom Title=USGS 3m DEM
Program Version=4.10

River Reach=RckhsCrk1       ,Main
Reach XY= 30
     1868551.218      269052.301     1868400.176      269592.666
     1867986.456       270121.56      1868055.97      270447.032
     1867531.687      270816.625      1866896.27      271593.968
     1866624.135      271673.395     1866728.301      272330.947
     1866547.874      272372.792     1866560.332      272758.031
     1866031.687      273248.916     1866040.801      273510.635
      1865490.02      273715.062     1865579.864       273876.52
     1865462.676      273875.218      1865166.44      274984.463
     1864618.465      275059.967     1864191.418      275363.564
     1864178.897      275747.134     1863933.342       276191.62
     1863335.852      276719.802     1863210.072      277172.093
     1862410.593      277919.489     1862163.197      278511.937
     1861592.515      278939.313     1861323.353      279665.583
     1860982.207       279751.52     1860430.124      280446.833
     1860213.953       281308.94     1860196.589      283927.897

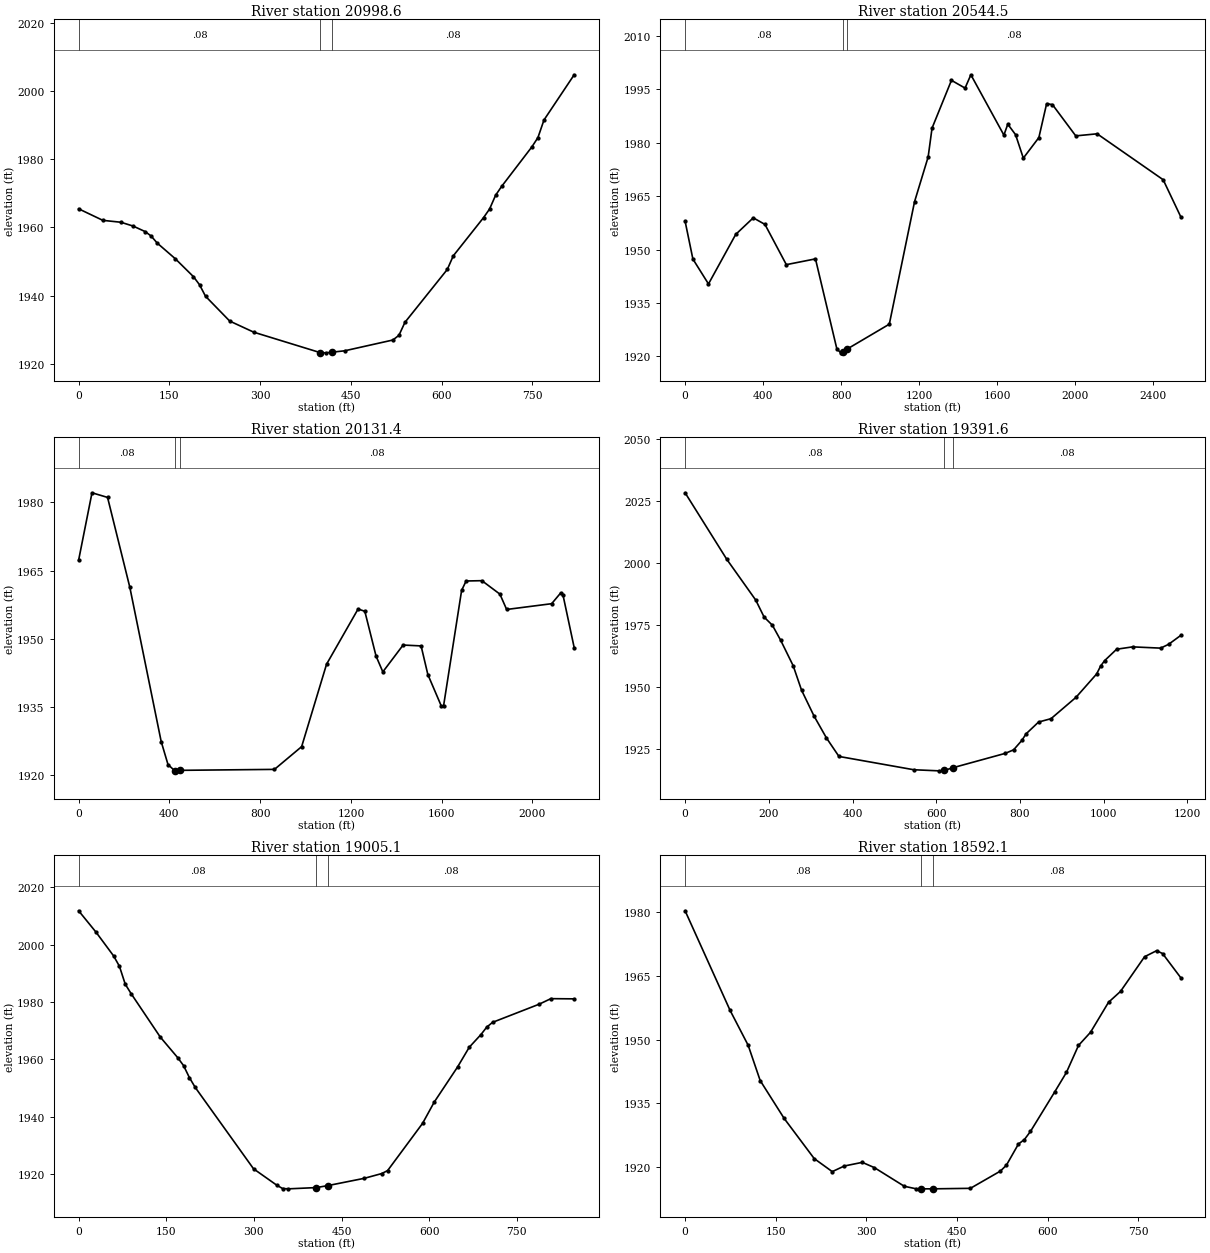
Type RM Length L Ch R = 1 ,20998.6 ,449.2,454,458.8
XS GIS Cut Line= 3
     1868141.608      269049.096     1868550.895      269062.296
     1868960.183      269075.496
#Sta/Elev= 30
       0 1965.41      40 1962.03    69.9 1961.47    89.9 1960.36   109.9 1958.74
   119.8 1957.44   129.8 1955.38   159.8 1950.77   189.8 1945.52   199.8 1943.16
   209.7 1939.79   249.7 1932.51   289.6 1929.24   399.5 1923.25   409.5  1923.2
   419.5 1923.41   439.5 1923.79   519.4 1926.96   529.4 1928.34   539.3 1932.14
   609.3 1947.64   619.2 1951.63   669.2 1962.82   679.2 1965.36   689.2  1969.4
   699.2    1972   749.1 1983.56   759.1 1986.28   769.1 1991.44     819 2004.69
#Mann= 3 , 0 , 0
       0     .08       0   399.5    .045       0   419.5     .08       0
Bank Sta=399.5,419.5
XS Rating Curve= 0 ,0
Exp/Cntr=0.3,0.1

Type RM Length L Ch R = 1 ,20544.5 ,401,413.1,425.2
XS GIS Cut Line= 4
     1867619.768      269338.979     1868036.445         269388.
     1868737.952      269538.203     1869950.709      270246.477
#Sta/Elev= 30
       0 1957.97      40 1947.34   119.9 1940.35   259.7 1954.27   349.6 1958.92
   409.6 1957.07   519.2 1945.77   668.6 1947.39   778.2 1922.13   798.2    1921
   808.8 1921.11   828.8 1921.99  1047.3 1929.05  1176.8 1963.46  1246.5 1976.02
  1266.4  1984.1    1366 1997.54  1435.8 1995.36  1465.6  1999.1    1635 1982.16
  1654.9 1985.22  1694.8 1982.28  1734.6 1975.69  1814.3 1981.46  1854.1 1990.98
    1884 1990.72  2003.5 1981.94  2113.1 1982.52  2451.8 1969.62  2541.4 1959.29
#Mann= 3 , 0 , 0
       0     .08       0   808.8    .045       0   828.8     .08       0
Bank Sta=808.8,828.8
XS Rating Curve= 0 ,0
Exp/Cntr=0.3,0.1

Type RM Length L Ch R = 1 ,20131.4 ,746,739.6,733.1
XS GIS Cut Line= 4
     1867971.725      269413.216     1868094.045      269702.346
     1868697.001      270195.006     1869719.085      270577.368
#Sta/Elev= 30
       0  1967.3    58.9  1982.1   127.5 1981.08   225.6 1961.33   363.8 1927.42
   393.8 1922.37   423.8 1920.98     426 1920.98     446 1921.09     863  1921.3
   982.8  1926.3  1092.6 1944.42  1231.5 1956.55  1261.2 1956.05  1310.8 1946.19
  1340.6 1942.73  1429.9 1948.63  1509.2 1948.44    1539 1942.14  1598.5  1935.2
  1608.4  1935.3  1687.8 1960.65  1707.6 1962.71  1777.1 1962.78  1856.5 1959.82
  1886.2 1956.45  2084.6 1957.72  2124.3 1960.08  2134.2  1959.7  2183.8 1948.08
#Mann= 3 , 0 , 0
       0     .08       0     426    .045       0     446     .08       0
Bank Sta=426,446
XS Rating Curve= 0 ,0
Exp/Cntr=0.3,0.1

Type RM Length L Ch R = 1 ,19391.6 ,381.7,386.5,391.2
XS GIS Cut Line= 3
     1867513.148      270136.181     1868380.817      270577.368
     1868549.939      270702.371
#Sta/Elev= 30
       0 2028.17    99.3 2001.44   168.8 1984.94   188.7 1978.12   208.6  1974.8
   228.4 1968.73   258.2  1958.5   278.1  1948.7   307.9 1938.28   337.7 1929.41
   367.5 1921.98   546.3 1916.62   605.9 1916.18   618.8 1916.33   638.8 1917.39
   764.8 1923.22   784.7 1924.64   804.5 1928.45   814.5 1931.08   844.3 1935.83
   874.1 1937.19   933.7 1945.78     983 1955.19   992.5 1958.36  1002.1 1960.56
  1030.8 1965.16    1069 1966.11  1135.9  1965.6    1155 1967.14  1183.7 1970.69
#Mann= 3 , 0 , 0
       0     .08       0   618.8    .045       0   638.8     .08       0
Bank Sta=618.8,638.8
XS Rating Curve= 0 ,0
Exp/Cntr=0.3,0.1

Type RM Length L Ch R = 1 ,19005.1 ,414.5,412.8,409.3
XS GIS Cut Line= 2
     1867454.761      270385.513      1868120.46       270911.11
#Sta/Elev= 30
       0  2011.8    29.9 2004.31    59.9 1996.06    69.8 1992.47    79.8 1986.21
    89.8 1982.93   139.7  1967.8   169.6  1960.6   179.6 1957.84   189.6 1953.65
   199.6 1950.22   299.4 1921.86   339.3 1916.13   349.2 1914.98   359.2 1914.88
   407.1 1915.32   427.1 1916.03     489 1918.55   518.9 1920.21   528.9 1921.25
   588.7  1937.7   608.7 1945.13   648.6 1957.35   668.6 1964.23   688.5 1968.62
   698.5 1971.24   708.5 1972.91   788.3 1979.24   808.3 1981.17   848.2  1981.1
#Mann= 3 , 0 , 0
       0     .08       0   407.1    .045       0   427.1     .08       0
Bank Sta=407.1,427.1
XS Rating Curve= 0 ,0
Exp/Cntr=0.3,0.1

Type RM Length L Ch R = 1 ,18592.1 ,493.9,502.8,511.7
XS GIS Cut Line= 3
     1867207.993      270621.487     1867248.436      270658.252
     1867828.181      271158.296
#Sta/Elev= 30
       0 1980.31    74.5 1956.87   104.4 1948.67   124.3 1940.37     164 1931.46
   213.7 1922.02   243.6 1918.95   263.5 1920.27   293.3 1921.13   313.2  1919.9
   362.9  1915.5   382.8  1914.9   390.2  1914.9   410.2  1914.9   472.3 1915.02
     522 1919.08   531.9 1920.47   551.8 1925.44   561.7  1926.5   571.7  1928.4
   611.5 1937.62   631.3  1942.3   651.2 1948.63   671.1 1951.72   700.9 1958.78
   720.8 1961.35   760.6  1969.5   780.5 1970.92   790.4 1970.25   820.3  1964.6
#Mann= 3 , 0 , 0
       0     .08       0   390.2    .045       0   410.2     .08       0
Bank Sta=390.2,410.2
XS Rating Curve= 0 ,0
Exp/Cntr=0.3,0.1

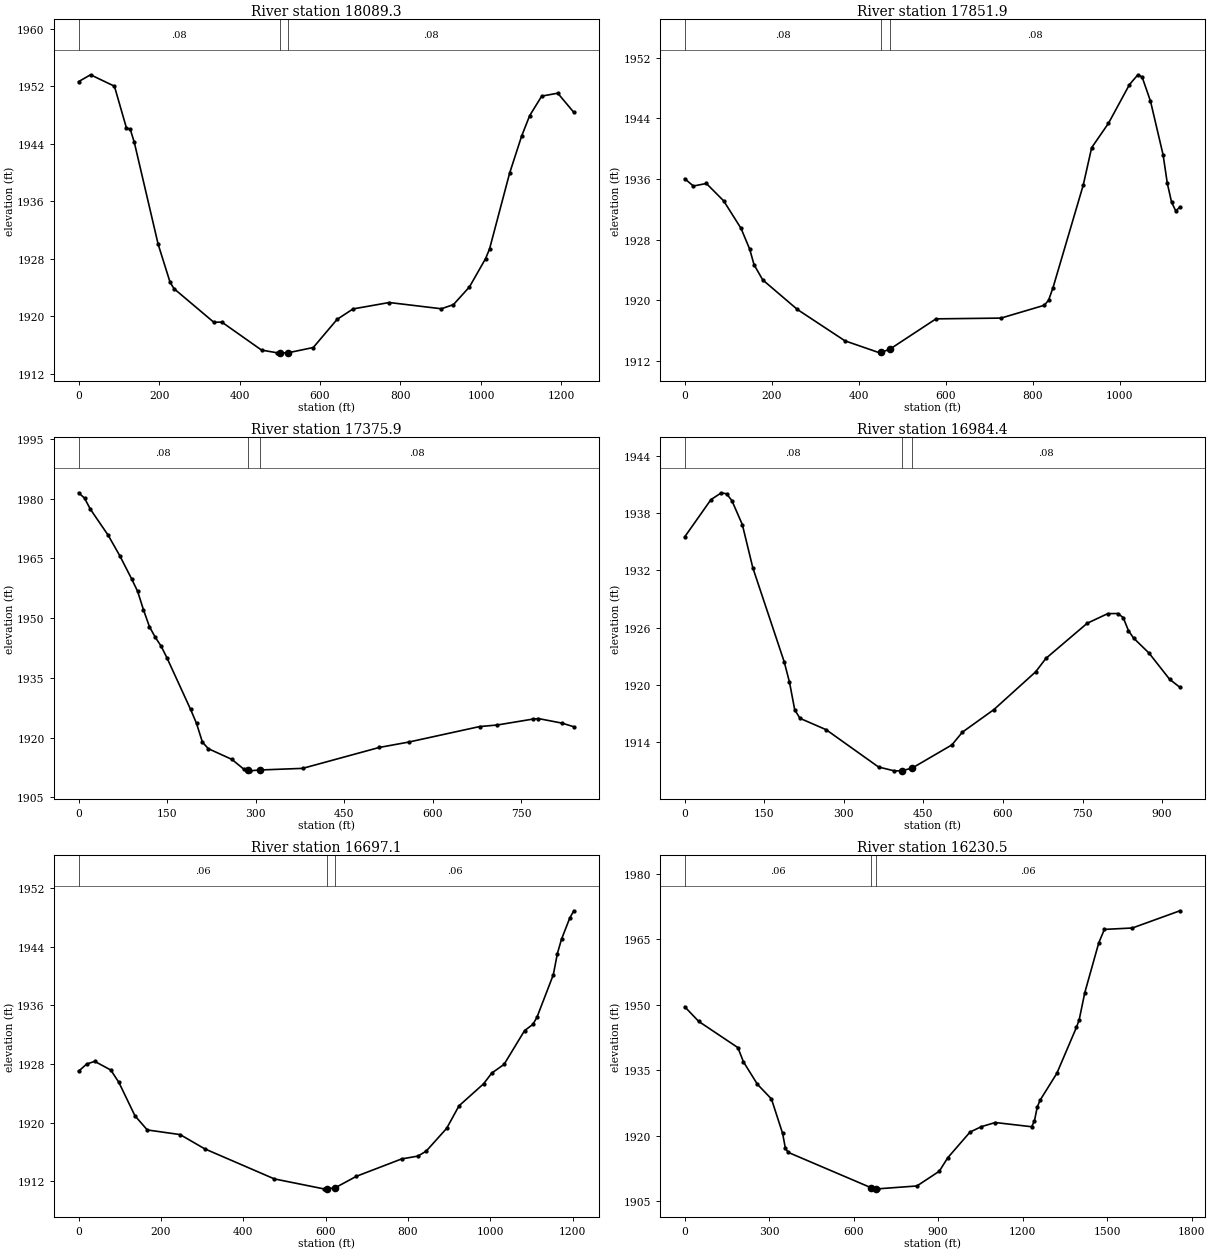
Type RM Length L Ch R = 1 ,18089.3 ,252.8,237.9,223.1
XS GIS Cut Line= 3
     1866918.464      270755.222     1867224.538      271342.553
     1867731.904      271598.993
#Sta/Elev= 30
       0 1952.63    29.7 1953.58      89 1951.99   118.6 1946.23   128.5 1945.97
   138.4 1944.18   197.7    1930   227.4  1924.7   237.2 1923.82   336.1 1919.15
   355.9 1919.18   454.7 1915.28   494.2  1914.9   499.9  1914.9   519.9  1914.9
   583.2 1915.64   642.5 1919.56   682.2 1921.01     772  1921.9   901.7 1921.03
   931.6 1921.61   971.5 1924.08  1011.4    1928  1021.3 1929.34  1071.2 1939.89
  1101.1 1945.05  1121.1  1947.9    1151 1950.61  1190.9 1951.02  1230.8 1948.35
#Mann= 3 , 0 , 0
       0     .08       0   499.9    .045       0   519.9     .08       0
Bank Sta=499.9,519.9
XS Rating Curve= 0 ,0
Exp/Cntr=0.3,0.1

Type RM Length L Ch R = 1 ,17851.9 ,475.6,475.2,472
XS GIS Cut Line= 3
     1866620.663      271144.018     1867395.498      271632.082
     1867591.275      271736.864
#Sta/Elev= 30
       0 1936.05    19.9 1935.08    49.8 1935.42    89.6 1933.12   129.4  1929.5
   149.3 1926.76   159.3 1924.71   179.2 1922.71   258.8 1918.81   368.3 1914.67
   447.9 1913.09   451.3 1913.15   471.3 1913.57   577.3 1917.57   726.6 1917.67
   826.2 1919.36   836.1 1920.04   846.1 1921.66   915.7 1935.21     935 1940.14
   973.7 1943.36  1021.9 1948.46  1041.2 1949.75  1050.9 1949.46  1070.2 1946.27
  1099.2 1939.18  1108.8 1935.45  1118.5 1932.98  1128.1 1931.81  1137.8  1932.3
#Mann= 3 , 0 , 0
       0     .08       0   451.3    .045       0   471.3     .08       0
Bank Sta=451.3,471.3
XS Rating Curve= 0 ,0
Exp/Cntr=0.3,0.1

Type RM Length L Ch R = 1 ,17375.9 ,406.4,391.5,379.1
XS GIS Cut Line= 2
     1866430.401      271455.607     1867139.879      271904.624
#Sta/Elev= 30
       0 1981.44      10  1980.1      20  1977.3      50 1970.81      70 1965.59
      90  1959.8     100 1956.73     110 1952.07     120 1947.87   129.9  1945.2
   139.9 1942.96   149.9 1939.99   189.9 1927.08   199.9 1923.58   209.9 1918.88
   219.9 1917.24   259.9 1914.55   279.9 1912.12   286.7 1911.82   289.9 1911.68
   306.7 1911.89   379.8  1912.3   509.8 1917.55   559.8  1918.9   679.7 1922.78
   709.7 1923.18   769.7 1924.65   779.7 1924.79   819.6 1923.65   839.6 1922.74
#Mann= 3 , 0 , 0
       0     .08       0   286.7    .045       0   306.7     .08       0
Bank Sta=286.7,306.7
XS Rating Curve= 0 ,0
Exp/Cntr=0.3,0.1

Type RM Length L Ch R = 1 ,16984.4 ,279.6,287.2,294.8
XS GIS Cut Line= 3
     1866262.511      271969.211     1866912.949      271927.126
     1867194.206       271943.67
#Sta/Elev= 30
       0 1935.51    49.4 1939.41    69.1 1940.13      79 1940.02    88.9 1939.31
   108.6  1936.8   128.4 1932.27   187.6 1922.41   197.5 1920.29   207.4 1917.39
   217.3  1916.5   266.6 1915.31   365.4  1911.4     395    1911   409.1    1911
   429.1  1911.3   503.7 1913.72   523.4 1915.05   582.7 1917.41   661.5 1921.37
   680.9 1922.78   758.7 1926.46   797.5 1927.47     817 1927.48   826.7 1927.04
   836.4  1925.7   846.1 1924.91   875.2 1923.34   914.1 1920.59   933.5 1919.75
#Mann= 3 , 0 , 0
       0     .08       0   409.1    .045       0   429.1     .08       0
Bank Sta=409.1,429.1
XS Rating Curve= 0 ,0
Exp/Cntr=0.3,0.1

Type RM Length L Ch R = 1 ,16697.1 ,466.6,466.1,465.9
XS GIS Cut Line= 3
     1866143.629      272012.606     1866264.955      272076.027
     1867304.503      272310.408
#Sta/Elev= 30
       0 1927.02    19.6    1928    39.1 1928.36    78.2 1927.18    97.8 1925.49
   136.9 1920.94   166.8 1919.02   246.4 1918.39   306.2 1916.45   475.5 1912.35
     595    1911   603.6    1911   623.6 1911.16   674.7 1912.71   784.3 1915.07
   824.1 1915.46     844 1916.13   893.8 1919.24   923.7  1922.3   983.4  1925.3
  1003.4 1926.77  1033.2 1927.95    1083 1932.55    1103 1933.39  1112.9 1934.34
  1152.8 1940.16  1162.7 1943.05  1172.7    1945  1192.6 1947.86  1202.6 1948.87
#Mann= 3 , 0 , 0
       0     .06       0   603.6    .045       0   623.6     .06       0
Bank Sta=603.6,623.6
XS Rating Curve= 0 ,0
Exp/Cntr=0.3,0.1

Type RM Length L Ch R = 1 ,16230.5 ,499.9,511.9,523.2
XS GIS Cut Line= 3
     1865870.644      272343.497     1866868.831      272445.521
     1867621.607      272503.427
#Sta/Elev= 30
       0 1949.57    49.7  1946.2   188.8 1940.19   208.6 1936.92   258.3 1931.77
     308 1928.41   347.7  1920.5   357.6 1917.06   367.6 1916.16   660.5 1908.09
   680.5 1907.83   685.5  1907.8   824.6 1908.46     904 1911.84   933.8 1914.91
  1013.3 1920.83  1053.1 1922.05  1102.7 1923.01  1231.9 1922.04  1241.8 1923.36
  1251.7 1926.53  1261.7 1928.11  1321.3 1934.28  1390.8 1944.81  1400.8 1946.59
  1420.6 1952.79  1470.3 1964.23  1490.2  1967.3  1589.5 1967.62  1758.4 1971.57
#Mann= 3 , 0 , 0
       0     .06       0   660.5    .045       0   680.5     .06       0
Bank Sta=660.5,680.5
XS Rating Curve= 0 ,0
Exp/Cntr=0.3,0.1

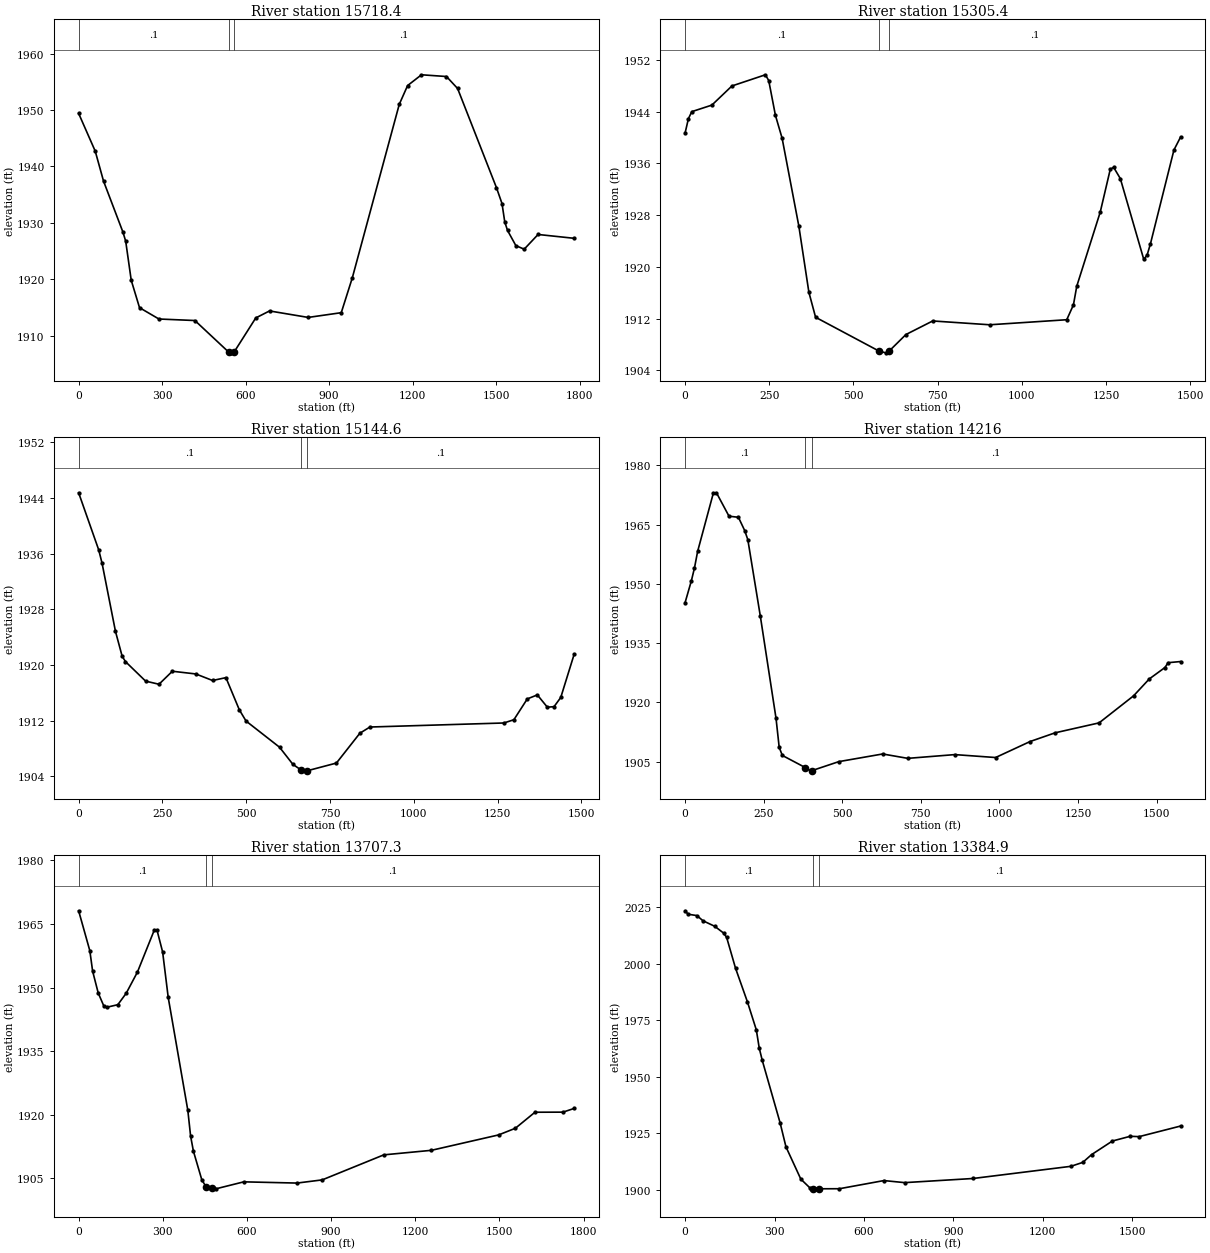
Type RM Length L Ch R = 1 ,15718.4 ,409.8,412.9,416
XS GIS Cut Line= 4
     1866008.515      272519.972     1866493.821      272867.407
     1866940.912      273081.041     1867626.202      273144.528
#Sta/Elev= 30
       0 1949.39    59.7 1942.69    89.5 1937.38   159.2 1928.34   169.1 1926.73
     189  1919.8   218.8 1914.94   288.5 1912.93   417.8 1912.66   539.6 1907.04
   547.1 1906.93   559.6 1907.14   636.5 1913.12     686 1914.36   824.8 1913.21
   943.7 1914.05   983.4 1920.23  1152.2 1951.01  1182.1 1954.33    1232 1956.24
  1321.8 1955.93  1361.7 1953.81  1501.3 1936.23  1521.3  1933.4  1531.2 1930.14
  1541.2 1928.63  1571.1 1925.94    1601 1925.31  1650.9 1927.92  1780.6 1927.24
#Mann= 3 , 0 , 0
       0      .1       0   539.6    .045       0   559.6      .1       0
Bank Sta=539.6,559.6
XS Rating Curve= 0 ,0
Exp/Cntr=0.3,0.1

Type RM Length L Ch R = 1 ,15305.4 ,174.4,159,132.6
XS GIS Cut Line= 3
     1865754.832      272736.429     1866240.138      273192.323
     1866949.715      273574.685
#Sta/Elev= 30
       0  1940.7     9.9 1942.92    19.9    1944    79.5 1945.01   139.1 1947.97
   238.5  1949.7   248.4 1948.81   268.3 1943.43   288.2 1939.88   337.9 1926.28
   367.7 1916.06   387.6  1912.2   576.4 1906.96   596.3  1906.7   606.2 1906.98
   655.9 1909.53   735.5 1911.63   904.7 1911.04  1133.6 1911.82  1153.5 1914.12
  1163.4 1917.01  1233.1 1928.47  1262.9 1935.09  1272.9 1935.39  1292.8 1933.64
  1362.4 1921.15  1372.4 1921.83  1382.3 1923.58    1452 1938.07  1471.9 1940.09
#Mann= 3 , 0 , 0
       0      .1       0   576.4    .045       0   606.2      .1       0
Bank Sta=576.4,606.2
XS Rating Curve= 0 ,0
Exp/Cntr=0.3,0.1

Type RM Length L Ch R = 1 ,15144.6 ,923.8,930.1,947
XS GIS Cut Line= 2
      1865468.06      272923.934     1866787.946      273589.392
#Sta/Elev= 30
       0 1944.75    59.9 1936.54    69.9 1934.62   109.9 1924.82   129.8 1921.25
   139.8 1920.47   199.8 1917.67   239.7 1917.22   279.6 1919.09   349.6  1918.7
   399.5 1917.76   439.4 1918.17   479.4 1913.54   499.4 1911.93   599.2 1908.17
   639.2  1905.7   661.9 1904.95   679.2 1904.77   681.9 1904.78     769 1905.89
     839 1910.18   868.9 1911.07  1268.4 1911.65  1298.4 1912.12  1338.3 1915.11
  1368.3 1915.69  1398.2 1913.92  1418.2    1914  1438.2 1915.32  1478.2 1921.54
#Mann= 3 , 0 , 0
       0      .1       0   661.9    .045       0   681.9      .1       0
Bank Sta=661.9,681.9
XS Rating Curve= 0 ,0
Exp/Cntr=0.3,0.1

Type RM Length L Ch R = 1 ,14216   ,470.3,508.2,506.6
XS GIS Cut Line= 2
     1865140.846      273548.949     1866593.088      274162.935
#Sta/Elev= 30
       0 1945.27      20  1950.8    29.9 1954.06    39.9 1958.24    89.8 1972.97
    99.8 1973.07   139.7 1967.14   169.6 1966.87   189.6 1963.51   199.6  1961.2
   239.5 1941.78   289.4 1915.93   299.4 1908.62   309.4 1906.58   382.9 1903.49
   399.2 1902.68   402.9 1902.72     489 1905.01   628.7 1906.95   708.5 1905.84
   858.2 1906.79   987.9 1906.05  1097.7  1910.1  1177.5 1912.31  1317.2 1914.82
    1427 1921.67  1476.9 1925.94  1526.8 1928.84  1536.8 1930.06  1576.7 1930.35
#Mann= 3 , 0 , 0
       0      .1       0   382.9    .045       0   402.9      .1       0
Bank Sta=382.9,402.9
XS Rating Curve= 0 ,0
Exp/Cntr=0.3,0.1

Type RM Length L Ch R = 1 ,13707.3 ,322.8,322.1,323
XS GIS Cut Line= 2
     1865058.554      273873.855     1866721.768       274468.09
#Sta/Elev= 30
       0 1968.09    39.9 1958.68    49.9 1953.85    69.8 1948.71    89.8 1945.64
    99.8 1945.34   139.7 1945.95   169.6 1948.65   209.6 1953.64   269.4  1963.5
   279.4 1963.51   299.4 1958.37   319.3 1947.66   389.2 1921.04   399.1 1914.98
   409.1 1911.42     439 1904.68     454 1903.03     474 1902.63   488.9 1902.54
   588.7 1904.19   778.3  1903.9   868.1 1904.65  1087.6 1910.55  1257.3 1911.62
  1496.8 1915.25  1556.6 1916.82  1626.5  1920.6  1726.3 1920.62  1766.2  1921.5
#Mann= 3 , 0 , 0
       0      .1       0     454    .045       0     474      .1       0
Bank Sta=454,474
XS Rating Curve= 0 ,0
Exp/Cntr=0.3,0.1

Type RM Length L Ch R = 1 ,13384.9 ,370.8,371.7,372.3
XS GIS Cut Line= 2
     1864971.477      274149.957      1866526.91      274736.479
#Sta/Elev= 30
       0 2023.45      10 2021.92    39.8 2021.32    59.7 2019.05    99.5 2016.57
   129.4 2013.55   139.4 2011.64   169.2    1998     209 1983.14   238.9 1970.72
   248.8 1962.58   258.8 1957.22   318.5 1929.64   338.4 1918.88   388.2 1904.61
   418.1  1900.8   429.3 1900.33     438  1900.3   449.3 1900.32   517.6 1900.35
   666.9 1903.96   736.6 1903.05   965.6 1904.88    1294 1910.27  1333.9 1912.01
  1363.7 1915.47  1433.4 1921.48  1493.1 1923.57    1523 1923.42  1662.3 1928.12
#Mann= 3 , 0 , 0
       0      .1       0   429.3    .045       0   449.3      .1       0
Bank Sta=429.3,449.3
XS Rating Curve= 0 ,0
Exp/Cntr=0.3,0.1

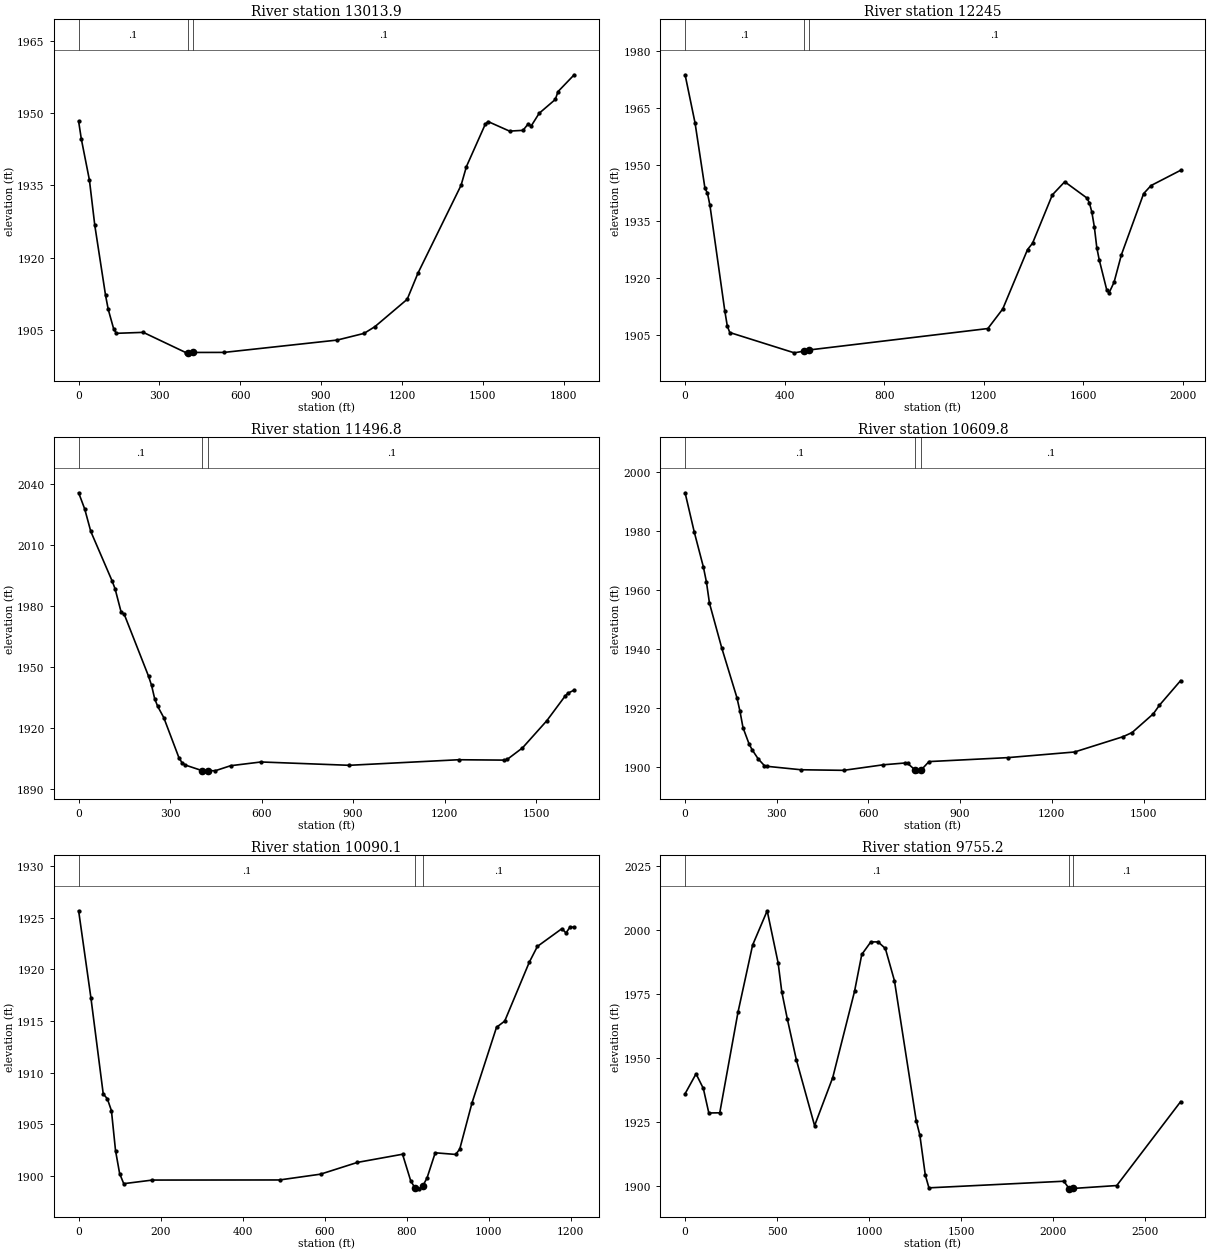
Type RM Length L Ch R = 1 ,13013.9 ,749.5,767.6,786.3
XS GIS Cut Line= 2
     1864843.515      274461.154     1866563.676      275111.488
#Sta/Elev= 30
       0 1948.25      10 1944.59      40 1936.09      60 1926.67     100 1912.12
   109.9 1909.23   129.9 1905.22   139.9 1904.27   239.9 1904.47   399.8 1900.22
   405.2 1900.25   425.2  1900.3   539.7 1900.31   959.5 1902.87  1059.4 1904.26
  1099.4 1905.65  1219.3 1911.33  1259.3 1916.76  1419.2 1934.98  1439.2 1938.88
  1509.2 1947.67  1519.2 1948.22  1599.1 1946.23  1649.1 1946.39  1669.1 1947.78
  1679.1 1947.26  1709.1 1949.93    1769  1952.8    1779 1954.43    1839 1957.92
#Mann= 3 , 0 , 0
       0      .1       0   405.2    .045       0   425.2      .1       0
Bank Sta=405.2,425.2
XS Rating Curve= 0 ,0
Exp/Cntr=0.3,0.1

Type RM Length L Ch R = 1 ,12245   ,745.1,745.7,730.6
XS GIS Cut Line= 3
     1864707.708      274641.635     1865368.793      275982.834
     1865802.628       276221.81
#Sta/Elev= 30
       0 1973.78    39.9 1961.06    79.8 1943.72    89.7 1942.49    99.7 1939.24
   159.5 1911.28   169.5 1907.29   179.4 1905.56   438.6 1900.18   479.2 1900.66
   499.2 1900.95  1216.2 1906.61    1276 1911.79  1375.6 1927.52  1395.6 1929.18
  1475.3    1942    1525 1945.46  1614.2 1941.16    1624 1939.89    1634 1937.42
  1643.9 1933.53  1653.8 1928.04  1663.7 1924.76  1693.4 1916.94  1703.3 1916.08
  1723.1 1918.86  1752.8 1926.17    1842 1942.33  1871.7 1944.46  1990.6  1948.5
#Mann= 3 , 0 , 0
       0      .1       0   479.2    .045       0   499.2      .1       0
Bank Sta=479.2,499.2
XS Rating Curve= 0 ,0
Exp/Cntr=0.3,0.1

Type RM Length L Ch R = 1 ,11496.8 ,892.3,884.8,865.7
XS GIS Cut Line= 2
     1863995.478      275009.606     1865298.939      275979.157
#Sta/Elev= 30
       0 2035.78    19.9  2027.8    39.9  2016.7   109.6 1992.37   119.6 1988.38
   139.5 1976.86   149.5 1975.88   229.2 1945.35   239.2 1940.78   249.2 1934.31
   259.1 1930.52   279.1 1924.95   328.9 1905.14   338.9 1902.72   348.8 1901.61
   405.6 1898.77   418.6 1898.71   425.6 1898.72   448.5 1898.79   498.3 1901.24
     598 1903.08     887 1901.44  1245.8 1904.18  1395.3    1904  1405.2 1904.37
  1455.1 1910.03  1534.8 1923.42  1594.6 1935.54  1604.6 1937.02  1624.5 1938.52
#Mann= 3 , 0 , 0
       0      .1       0   405.6    .045       0   425.6      .1       0
Bank Sta=405.6,425.6
XS Rating Curve= 0 ,0
Exp/Cntr=0.3,0.1

Type RM Length L Ch R = 1 ,10609.8 ,525.7,517.1,524.3
XS GIS Cut Line= 3
     1863409.186      275372.524     1864072.184      275816.565
     1864780.543      276236.516
#Sta/Elev= 30
       0 1993.07    29.9 1979.79    59.8 1967.91    69.8 1962.81    79.8 1955.58
   119.7 1940.52   169.6 1923.57   179.5 1918.98   189.5 1913.39   209.5 1907.83
   219.4 1905.89   239.4 1902.77   259.3 1900.54   269.3 1900.27     379 1899.12
   518.7 1898.92   648.3  1900.8   718.2  1901.4   728.1 1901.29   752.3 1899.05
   758.1 1898.75   772.3 1899.04     798 1901.89  1055.9 1903.23  1274.2 1905.14
  1432.9 1910.33  1462.7 1911.75  1532.2 1918.11    1552 1921.01  1621.4 1929.36
#Mann= 3 , 0 , 0
       0      .1       0   752.3    .045       0   772.3      .1       0
Bank Sta=752.3,772.3
XS Rating Curve= 0 ,0
Exp/Cntr=0.3,0.1

Type RM Length L Ch R = 1 ,10090.1 ,323.8,335.3,339.8
XS GIS Cut Line= 3
     1863263.042      275677.219     1863867.396      276170.346
     1864220.426      276413.434
#Sta/Elev= 30
       0 1925.66      30 1917.22      60 1907.93      70 1907.46      80 1906.31
      90 1902.44     100 1900.22     110 1899.24     180 1899.59     490  1899.6
     590 1900.16     680  1901.3     790 1902.09   809.9 1899.52   819.9 1898.85
   829.8 1898.74   839.8 1899.05   849.8  1899.8   869.7 1902.23   919.6 1902.07
   929.5 1902.59   959.4 1907.06  1019.2 1914.38  1039.2 1914.98    1099 1920.67
  1118.9 1922.21  1178.7 1923.93  1188.7 1923.51  1198.7  1924.1  1208.6 1924.06
#Mann= 3 , 0 , 0
       0      .1       0   819.9    .045       0   839.8      .1       0
Bank Sta=819.9,839.8
XS Rating Curve= 0 ,0
Exp/Cntr=0.3,0.1

Type RM Length L Ch R = 1 ,9755.2  ,766.7,754,740.4
XS GIS Cut Line= 5
     1861994.536      275223.699      1862647.29      275274.783
     1863054.403      275690.876     1863301.646      276024.655
     1864070.967      276727.797
#Sta/Elev= 30
       0 1935.93    59.5 1943.71    99.2 1937.98     129 1928.39   188.5 1928.46
   287.7 1967.86   367.1 1994.11   446.4 2007.53   505.9  1987.1   525.8 1975.78
   555.5 1965.31   605.2 1949.12   704.1 1923.43   802.8 1942.25   921.2 1975.95
   960.6 1990.42    1010 1995.36  1049.4 1995.34  1088.9 1992.77  1138.2 1980.19
  1256.7 1925.38  1276.4 1919.74  1306.1  1904.1  1325.9 1899.09  2059.2 1901.68
    2089 1898.73  2098.9  1898.7  2111.4 1898.86  2347.1 1899.99  2694.5 1932.83
#Mann= 3 , 0 , 0
       0      .1       0    2089    .045       0  2111.4      .1       0
Bank Sta=2089,2111.4
XS Rating Curve= 0 ,0
Exp/Cntr=0.3,0.1

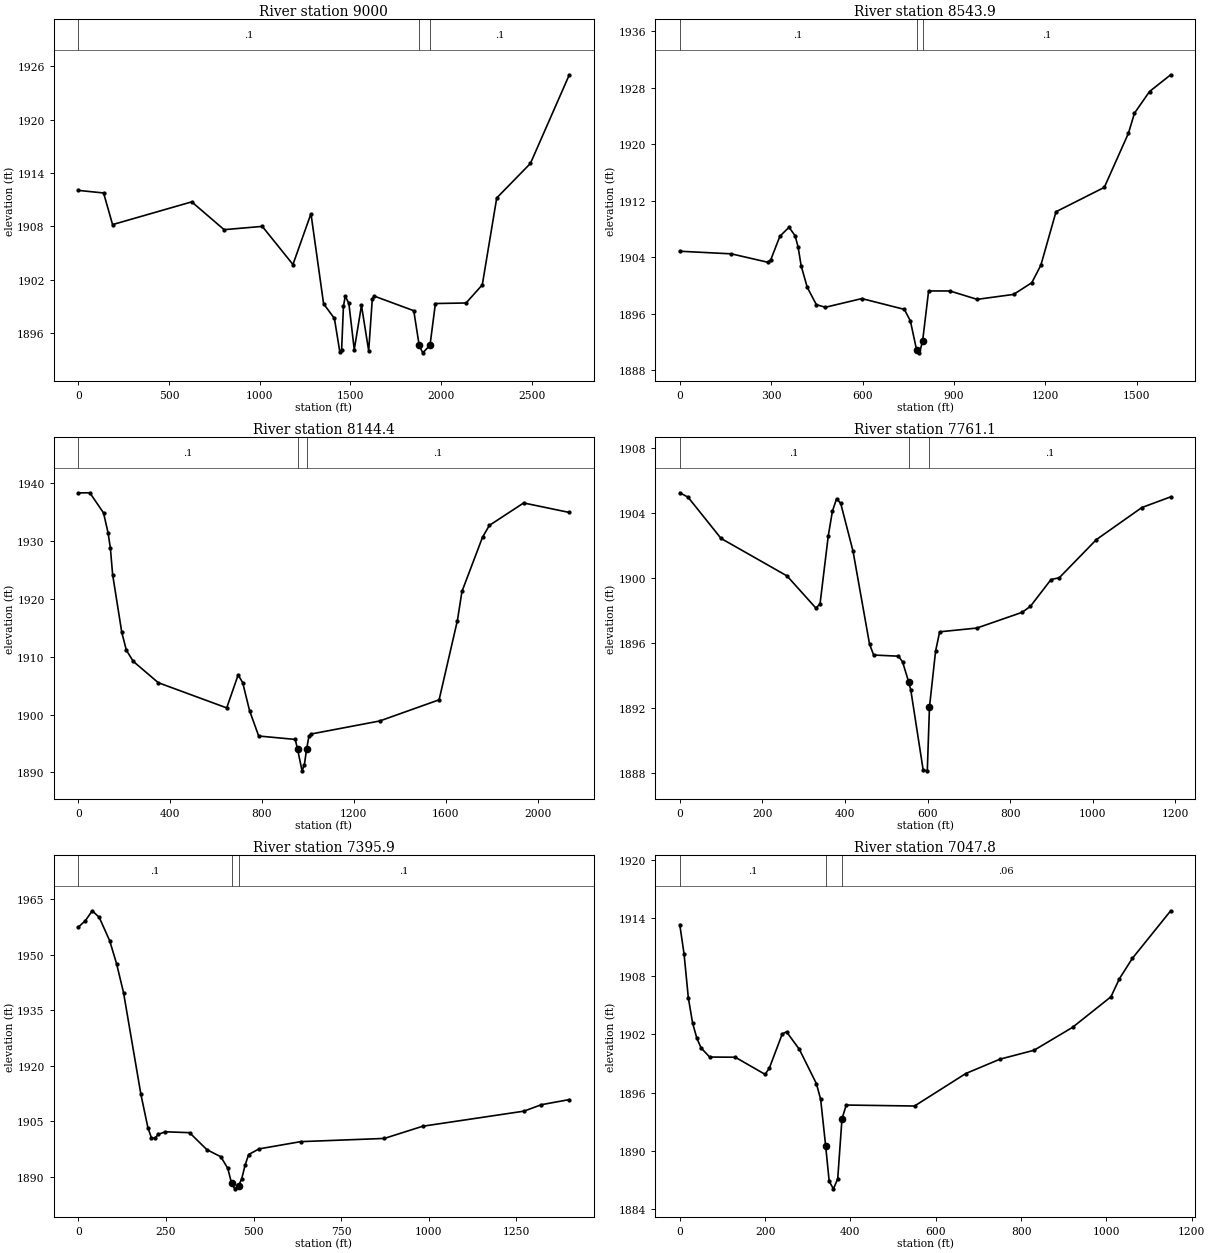
Type RM Length L Ch R = 1 ,9000    ,455.5,456,456.9
XS GIS Cut Line= 5
     1861634.739      275855.279     1862213.174      276468.865
     1862309.161       276610.18     1863551.318      277034.992
     1863786.497      277334.065
#Sta/Elev= 30
       0 1912.05   138.9 1911.76   188.5  1908.2     625 1910.76   803.6 1907.63
  1014.1    1908  1183.2 1903.71  1282.6 1909.43  1352.2 1899.29  1411.9 1897.64
  1441.7 1893.87  1451.7 1894.12  1461.6 1898.99  1471.6 1900.14  1491.5 1899.34
  1521.3 1894.13  1561.1  1899.1  1600.9    1894  1620.8 1899.84  1630.7 1900.16
  1849.5 1898.51  1879.3 1894.62  1899.2 1893.77    1939 1894.62  1968.8 1899.32
  2137.9 1899.38  2227.4 1901.42    2307  1911.2  2492.7 1915.08  2707.3 1925.06
#Mann= 3 , 0 , 0
       0      .1       0  1879.3    .045       0    1939      .1       0
Bank Sta=1879.3,1939
XS Rating Curve= 0 ,0
Exp/Cntr=0.3,0.1

Type RM Length L Ch R = 1 ,8543.9  ,392.5,399.4,406.3
XS GIS Cut Line= 3
     1862284.158      276998.024     1863456.062      277356.489
     1863820.041      277486.088
#Sta/Elev= 30
       0 1904.84   169.4 1904.47   288.9 1903.28   298.9 1903.65   328.8 1906.97
   358.7 1908.24   378.6 1907.04   388.6 1905.43   398.5 1902.78   418.5 1899.73
   448.4 1897.27   478.2  1896.9   597.8 1898.13   737.3  1896.6   757.2 1894.96
   777.4 1890.88   787.1 1890.44   797.4 1892.13     817 1899.21   886.8 1899.21
   976.4 1898.02    1096 1898.72  1155.8 1900.38  1185.6 1902.86  1235.4 1910.44
  1393.9 1913.89  1473.2 1921.57    1493 1924.41  1542.5 1927.48  1611.9 1929.85
#Mann= 3 , 0 , 0
       0      .1       0   777.4    .045       0   797.4      .1       0
Bank Sta=777.4,797.4
XS Rating Curve= 0 ,0
Exp/Cntr=0.3,0.1

Type RM Length L Ch R = 1 ,8144.4  ,374.1,382.5,390.9
XS GIS Cut Line= 3
     1861892.604      277188.286     1862601.261       277419.91
     1863811.769      278109.265
#Sta/Elev= 30
       0 1938.32    49.7 1938.34   109.4 1934.87   129.2 1931.43   139.2 1928.83
   149.1  1924.2   188.9 1914.23   208.8 1911.14   238.6 1909.21   347.9 1905.51
   646.1 1901.15   695.8 1906.84   715.7 1905.52   745.6 1900.68   785.4 1896.29
   944.6  1895.7   954.5 1894.04   974.4 1890.27   984.4 1891.32   994.3 1894.06
  1004.3 1896.25  1014.2 1896.64  1312.7 1898.89  1571.4 1902.55    1651 1916.25
  1670.9 1921.28  1760.5 1930.66  1790.3  1932.7  1939.6 1936.58  2138.6 1934.94
#Mann= 3 , 0 , 0
       0      .1       0   954.5    .045       0   994.3      .1       0
Bank Sta=954.5,994.3
XS Rating Curve= 0 ,0
Exp/Cntr=0.3,0.1

Type RM Length L Ch R = 1 ,7761.1  ,372,365.3,357.5
XS GIS Cut Line= 2
     1862212.465      277364.761     1862990.057      278263.681
#Sta/Elev= 30
       0 1905.24      20 1904.97    99.9 1902.43   259.7 1900.12   329.6 1898.14
   339.6  1898.4   359.6  1902.6   369.6 1904.11   379.5 1904.86   389.5  1904.6
   419.5 1901.64   459.4 1895.93   469.4 1895.25   529.4 1895.18   539.4 1894.83
   553.9 1893.62   559.3  1893.1   589.3 1888.17   599.3 1888.12  604.58 1892.05
   619.3 1895.48   629.2 1896.68   719.1 1896.91     829 1897.88     849 1898.25
   898.9  1899.9   918.9 1900.01  1008.8 1902.36  1118.7 1904.33  1188.6 1904.99
#Mann= 3 , 0 , 0
       0      .1       0   553.9    .045       0  604.58      .1       0
Bank Sta=553.9,604.58
XS Rating Curve= 0 ,0
Exp/Cntr=0.3,0.1

Type RM Length L Ch R = 1 ,7395.9  ,347.6,347.6,347.6
XS GIS Cut Line= 3
     1862012.477      277827.831     1862650.895      278189.231
     1863295.695      278361.944
#Sta/Elev= 30
       0 1957.51    19.8 1959.23    39.6 1961.92    59.5 1960.12    89.2 1953.83
     109 1947.58   128.9 1939.72   178.4 1912.23   198.3 1903.25   208.2 1900.55
   218.1 1900.35     228 1901.42   247.8 1902.12   317.2 1901.88   366.8 1897.27
   406.5 1895.36   426.3 1892.22     437 1888.26   446.1 1886.68     457 1887.52
   465.9 1889.33   475.9 1893.13   485.8 1895.95   515.5 1897.49   634.5 1899.45
   873.1 1900.32   982.7 1903.62  1271.6  1907.7  1321.4 1909.45  1401.1 1910.83
#Mann= 3 , 0 , 0
       0      .1       0     437    .045       0     457      .1       0
Bank Sta=437,457
XS Rating Curve= 0 ,0
Exp/Cntr=0.3,0.1

Type RM Length L Ch R = 1 ,7047.8  ,523.2,525.9,528.1
XS GIS Cut Line= 2
     1861884.331      278084.448     1862904.577      278616.631
#Sta/Elev= 30
       0 1913.31      10  1910.3      20 1905.79      30 1903.17      40  1901.6
      50  1900.6      70 1899.66   130.1 1899.64   200.1 1897.87   210.1 1898.54
   240.2 1902.04   250.2 1902.26   280.2 1900.46   320.2 1896.92   330.2  1895.3
   341.9 1890.51   350.2 1886.85   360.2 1886.07   370.2  1887.1   380.2 1893.29
   390.2 1894.71   550.3 1894.61   670.4 1897.96   750.5 1899.44   830.5 1900.36
   920.6 1902.72  1010.6 1905.87  1030.6 1907.74  1060.6 1909.82  1150.7 1914.74
#Mann= 3 , 0 , 0
       0      .1       0   341.9    .045       0   380.2     .06       0
#XS Ineff= 2 , 0
          243.66 1902.05
Permanent Ineff=
       F       F
Bank Sta=341.9,380.2
XS Rating Curve= 0 ,0
Exp/Cntr=0.3,0.1