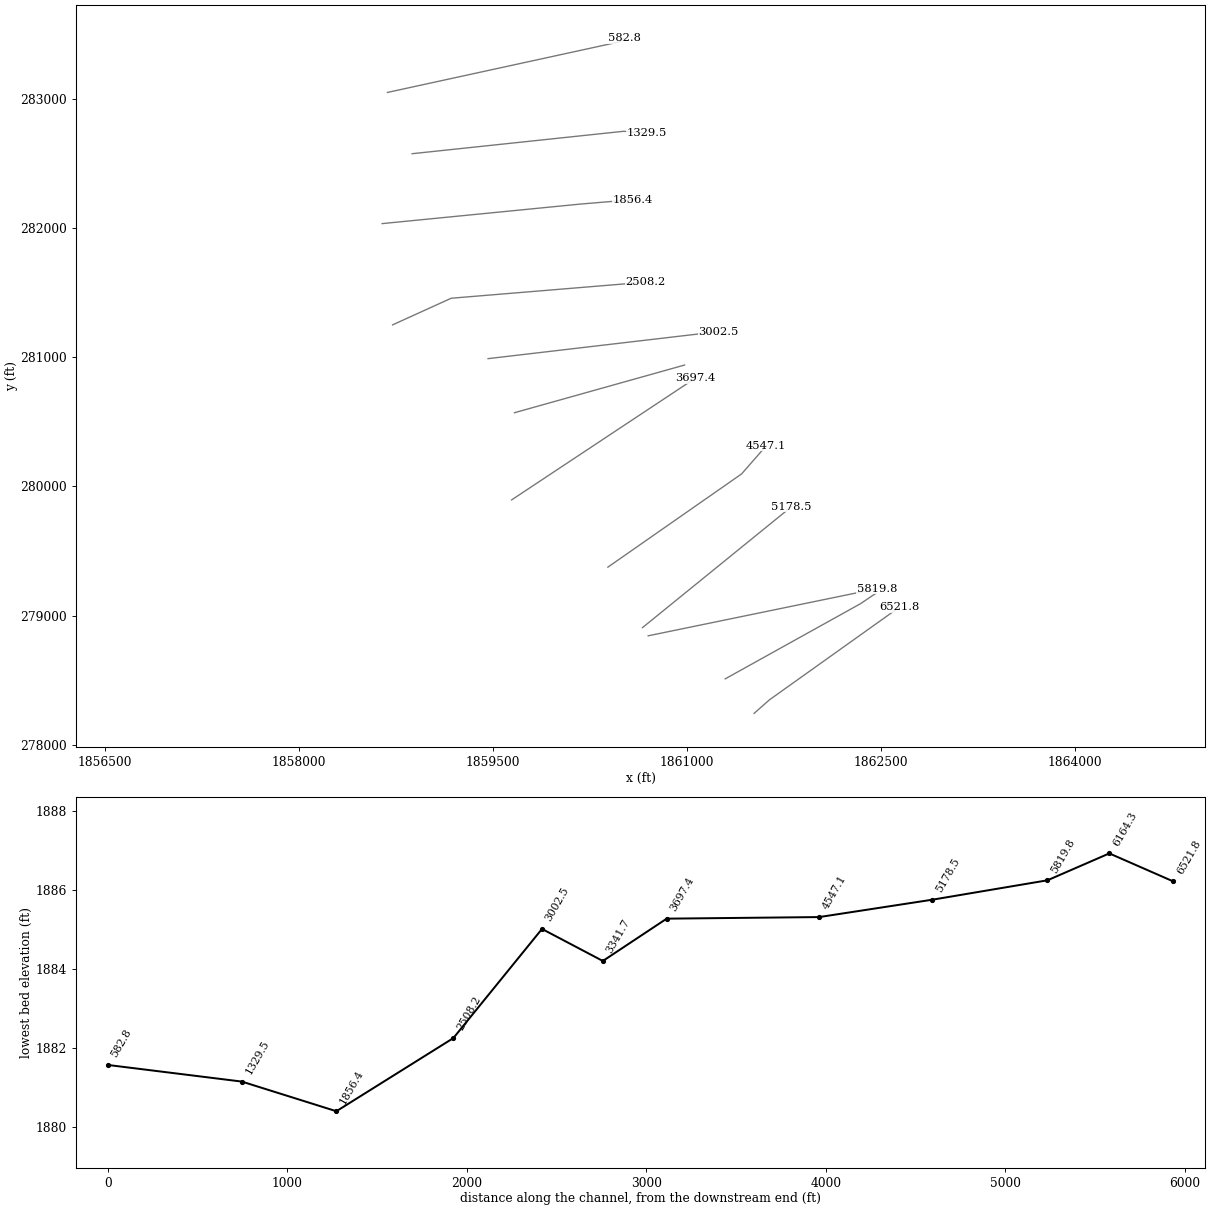
HEC-RAS study RckhsCrk1.prj: RckhsCrk1

--- RckhsCrk1.g01 (geometry) --- (continued)

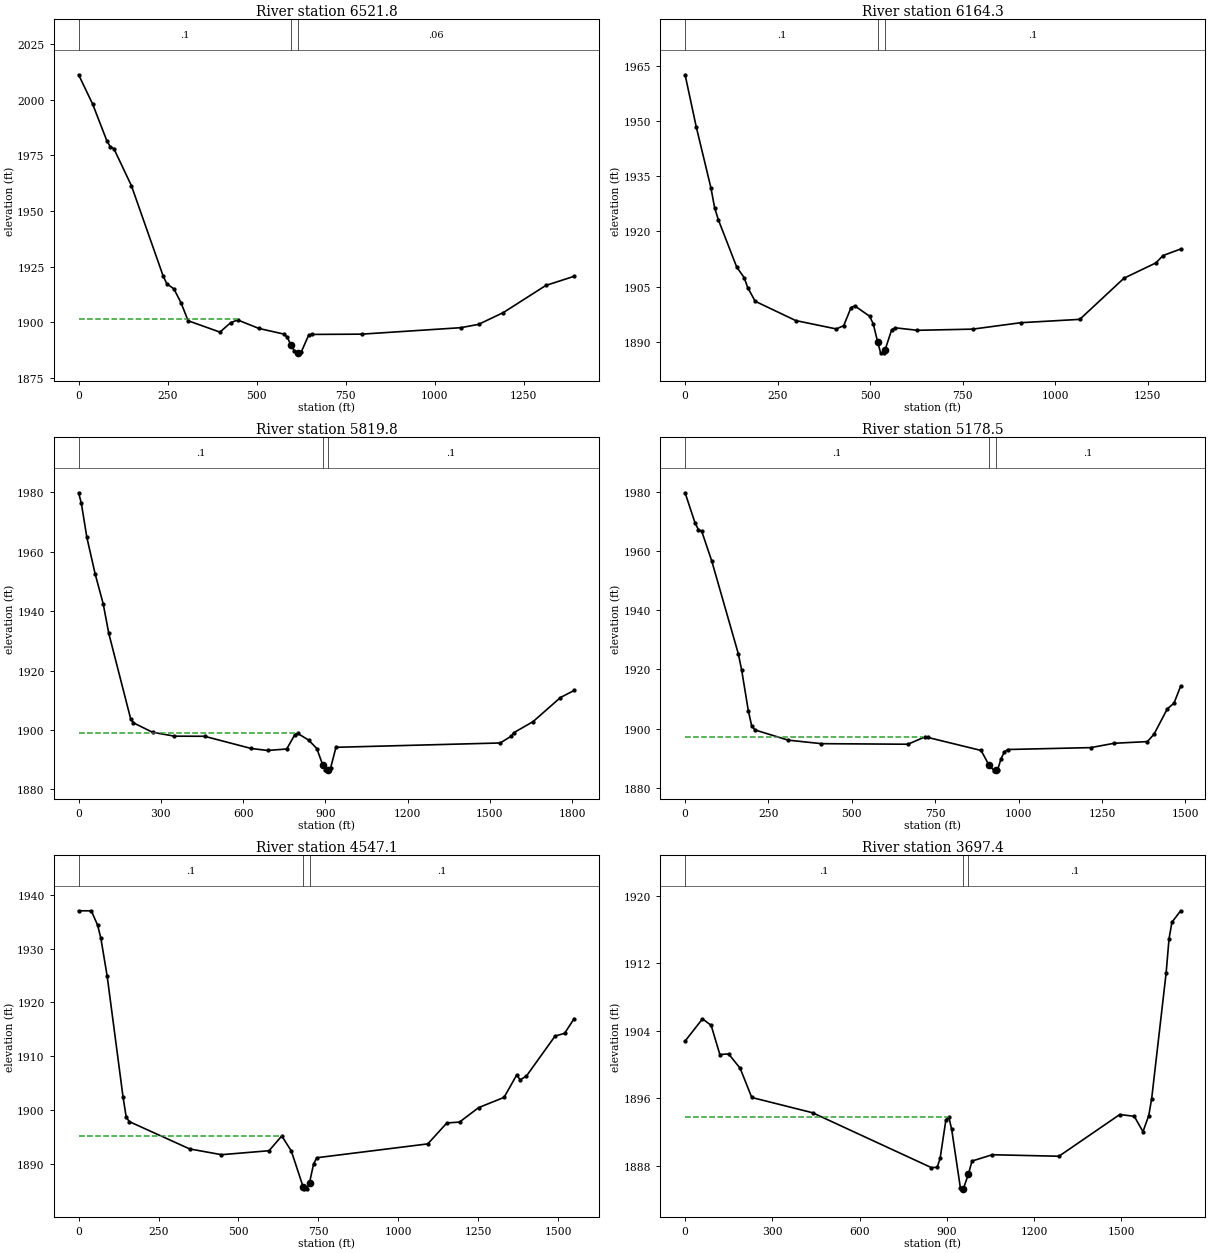
Type RM Length L Ch R = 1 ,6521.8  ,357.8,357.3,356.7
XS GIS Cut Line= 3
     1861517.594      278241.622     1861636.163      278346.404
     1862639.865      279063.333
#Sta/Elev= 30
       0 2011.21    39.6 1997.95    79.1  1981.6      89 1978.81    98.9 1978.04
   148.3 1961.32   237.8 1920.58   247.8 1917.24   267.6 1914.97   287.6  1908.7
   307.4 1900.65     397 1895.53   426.8 1899.77   446.7    1901   506.4 1897.18
     576 1894.67     586 1893.29   596.2 1889.63   605.9 1887.08   615.8 1886.22
   616.2 1886.24   625.8 1886.81   645.6 1894.03   655.6  1894.5   794.8 1894.62
  1073.4 1897.53  1123.1 1899.02  1192.7 1904.31  1312.1 1916.51  1391.7 1920.63
#Mann= 3 , 0 , 0
       0      .1       0   596.2    .045       0   616.2     .06       0
#XS Ineff= 2 , 0
          444.58 1901.28
Permanent Ineff=
       F       F
Bank Sta=596.2,616.2
XS Rating Curve= 0 ,0
Exp/Cntr=0.3,0.1

Type RM Length L Ch R = 1 ,6164.3  ,352.5,344.8,337
XS GIS Cut Line= 3
     1861294.243      278509.091     1862339.306      279090.907
     1862457.875      279170.873
#Sta/Elev= 30
       0 1962.68    29.9 1948.59    69.8 1931.88    79.7  1926.5    89.7 1923.22
   139.6 1910.27   159.5 1907.44   169.4 1904.66   189.4 1900.98     299 1895.72
   408.7 1893.44   428.6 1894.34   448.5 1899.27   458.5 1899.72   498.4 1896.92
   508.3 1894.88   520.6 1889.81   528.3 1886.93   538.2 1886.95   540.6 1887.78
   558.2 1893.22   568.2 1893.74     628 1893.07   777.5 1893.39     907 1895.14
  1066.5 1896.05  1186.1 1907.27  1272.4 1911.44  1291.4 1913.43  1339.1 1915.21
#Mann= 3 , 0 , 0
       0      .1       0   520.6    .045       0   540.6      .1       0
#XS Ineff= 2 , 0
          459.54 1899.51
Permanent Ineff=
       F       F
Bank Sta=520.6,540.6
XS Rating Curve= 0 ,0
Exp/Cntr=0.3,0.1

Type RM Length L Ch R = 1 ,5819.8  ,628.4,640.6,641.7
XS GIS Cut Line= 2
      1860698.64      278842.739     1862468.704      279208.014
#Sta/Elev= 30
       0 1979.84      10 1976.25      30 1964.82    59.9 1952.66    89.9 1942.35
   109.8 1932.58   189.7 1903.78   199.7 1902.41   269.6 1899.23   349.5 1897.92
   459.3 1897.88   629.1 1893.78     689 1893.11   758.9  1893.6   788.8 1898.46
   798.8 1898.86   838.8  1896.6   868.7 1893.76   890.1 1888.28   898.7 1886.65
   908.7 1886.25   910.1 1886.37   918.7  1887.1   938.6 1894.17  1537.8 1895.63
  1577.7 1897.91  1587.7 1899.12  1657.6 1902.82  1757.4 1910.93  1807.4 1913.32
#Mann= 3 , 0 , 0
       0      .1       0   890.1    .045       0   910.1      .1       0
#XS Ineff= 2 , 0
          799.21  1898.9
Permanent Ineff=
       F       F
Bank Sta=890.1,910.1
XS Rating Curve= 0 ,0
Exp/Cntr=0.3,0.1

Type RM Length L Ch R = 1 ,5178.5  ,633.6,631.4,626.3
XS GIS Cut Line= 2
     1860654.521       278906.16     1861807.124      279843.683
#Sta/Elev= 30
       0  1979.6    29.9  1969.4    39.9  1967.2    49.9 1966.59    79.8 1956.62
   159.5 1925.29   169.5 1919.83   189.5  1906.1   199.4 1901.04   209.4 1899.56
   309.1 1896.12   408.8 1894.93   668.1 1894.74   717.9 1897.16   727.9 1897.03
   887.5 1892.64   911.4 1887.64   927.3 1885.76   931.4 1885.93   937.3 1886.18
   947.3 1889.84   957.3 1892.12   967.2 1892.96  1216.5  1893.6  1286.3 1895.06
    1386 1895.63    1406 1898.12  1445.9  1906.7  1465.8 1908.58  1485.8 1914.33
#Mann= 3 , 0 , 0
       0      .1       0   911.4    .045       0   931.4      .1       0
#XS Ineff= 2 , 0
          717.79 1897.18
Permanent Ineff=
       F       F
Bank Sta=911.4,931.4
XS Rating Curve= 0 ,0
Exp/Cntr=0.3,0.1

Type RM Length L Ch R = 1 ,4547.1  ,852.6,849.7,846.8
XS GIS Cut Line= 3
     1860387.051      279374.922     1861421.085      280097.366
     1861611.347      280315.203
#Sta/Elev= 30
       0 1937.03    39.7 1937.02    59.6 1934.33    69.5 1931.94    89.4 1924.83
     139 1902.38     149 1898.62   158.9 1897.81   347.6 1892.74     447 1891.67
   595.9 1892.41   635.7 1895.16   665.5 1892.35   702.5 1885.68   705.2 1885.32
   715.1 1885.36   722.5 1886.47     735 1889.89   744.9  1891.1  1092.6 1893.68
  1152.2 1897.57  1191.9 1897.74  1251.5 1900.42  1331.2 1902.33  1371.1 1906.53
  1381.1 1905.58    1401 1906.28  1490.8 1913.73  1520.7 1914.24  1550.6 1916.98
#Mann= 3 , 0 , 0
       0      .1       0   702.5    .045       0   722.5      .1       0
#XS Ineff= 2 , 0
          635.68 1895.16
Permanent Ineff=
       F       F
Bank Sta=702.5,722.5
XS Rating Curve= 0 ,0
Exp/Cntr=0.3,0.1

Type RM Length L Ch R = 1 ,3697.4  ,363.5,355.7,347.8
XS GIS Cut Line= 2
     1859642.548      279896.075      1861062.62      280839.113
#Sta/Elev= 30
       0 1902.78    59.8 1905.41    89.7 1904.64   119.6 1901.18   149.5 1901.26
   189.4 1899.56   229.3  1896.1   438.6 1894.29   847.4 1887.79   867.3 1887.83
   877.3  1888.9   897.2 1893.45   907.2 1893.79   917.1 1892.31     947  1885.4
   954.4 1885.31     957 1885.28   974.4 1886.99   986.9 1888.57  1056.7 1889.32
    1286 1889.14  1495.3 1894.08  1545.2 1893.87  1575.1 1892.05    1595 1893.96
    1605 1895.95  1654.8 1910.85  1664.8  1914.9  1674.8 1916.86  1704.7 1918.21
#Mann= 3 , 0 , 0
       0      .1       0   954.4    .045       0   974.4      .1       0
#XS Ineff= 2 , 0
          907.25 1893.79
Permanent Ineff=
       F       F
Bank Sta=954.4,974.4
XS Rating Curve= 0 ,0
Exp/Cntr=0.3,0.1

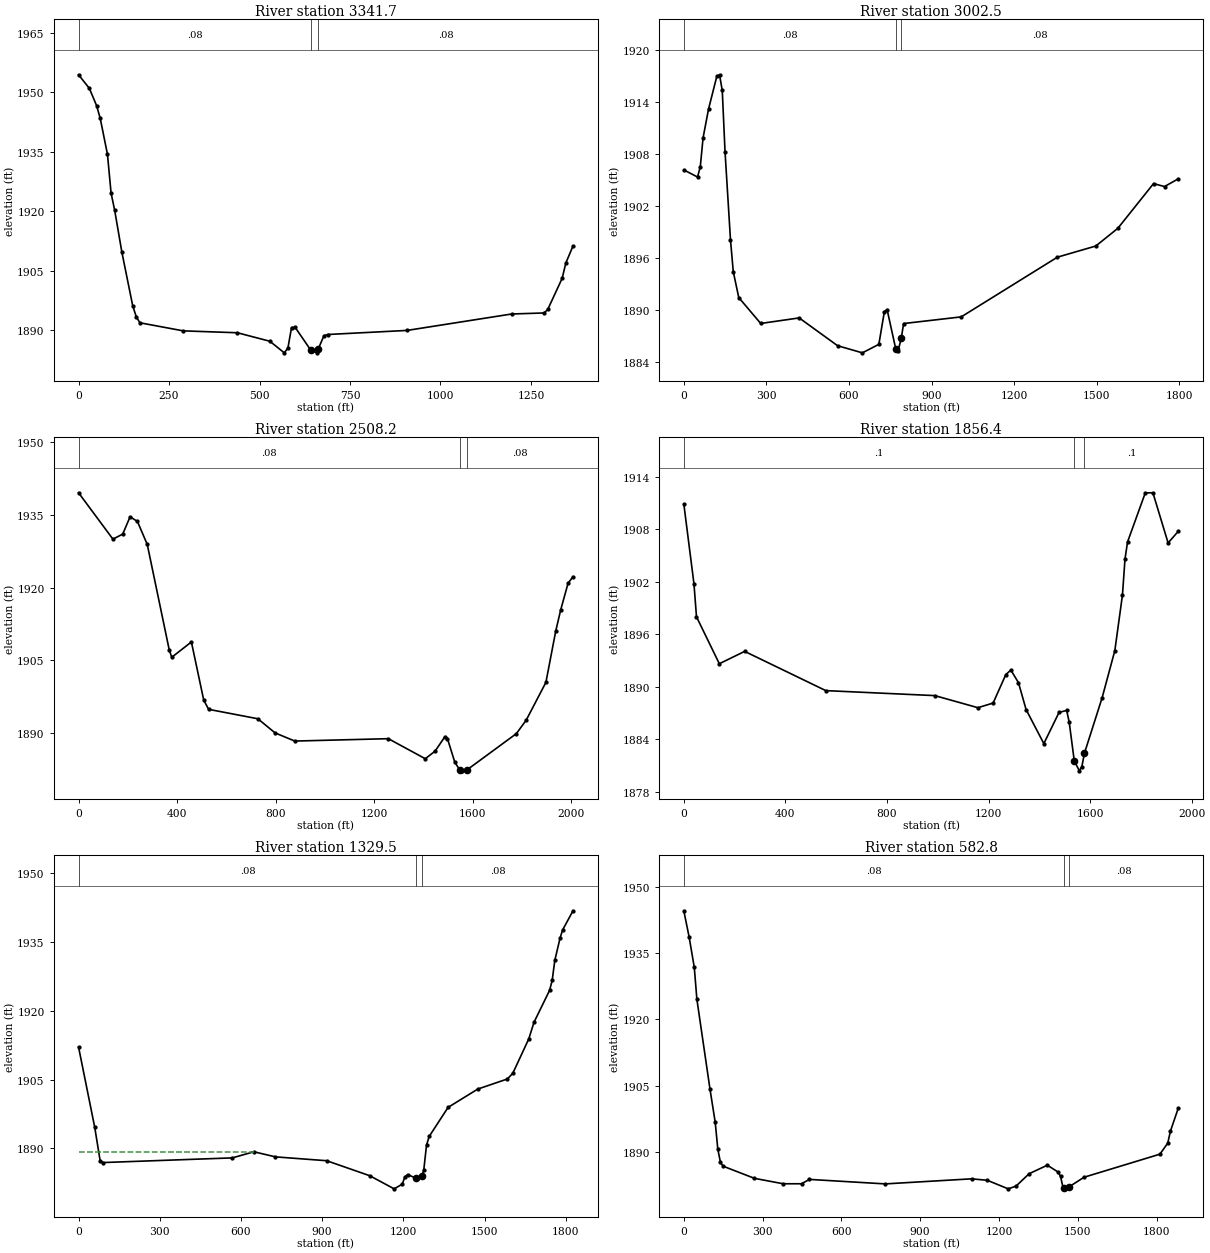
Type RM Length L Ch R = 1 ,3341.7  ,343,339.1,335.2
XS GIS Cut Line= 2
     1859664.607      280571.643     1860979.897      280941.137
#Sta/Elev= 30
       0 1954.43    29.9 1950.98    49.9 1946.61    59.8 1943.44    79.8 1934.34
    89.8 1924.56    99.7 1920.23   119.7  1909.6   149.6 1896.09   159.6 1893.28
   169.5  1891.8   289.2 1889.76   438.8 1889.28   528.5 1887.14   568.4 1884.21
   578.4 1885.41   588.4 1890.58   598.3 1890.66   642.2 1884.81   658.2 1884.25
   662.2  1885.2   678.1 1888.53   688.1 1888.84   907.5 1889.87  1196.7 1894.02
  1286.4 1894.28  1296.4 1895.17  1336.3 1903.04  1346.3 1906.87  1366.2  1911.2
#Mann= 3 , 0 , 0
       0     .08       0   642.2    .045       0   662.2     .08       0
Bank Sta=642.2,662.2
XS Rating Curve= 0 ,0
Exp/Cntr=0.3,0.1

Type RM Length L Ch R = 1 ,3002.5  ,494.3,493.8,492.8
XS GIS Cut Line= 2
     1859460.558      280990.771      1861244.61      281200.335
#Sta/Elev= 30
       0 1906.13    49.9 1905.31    59.9 1906.51    69.9 1909.82    89.8 1913.15
   119.8 1916.92   129.7 1917.11   139.7  1915.3   149.7 1908.25   169.6 1898.04
   179.6  1894.4   199.6  1891.4   279.4 1888.41   419.1 1889.05   558.8 1885.84
   648.7 1885.02   708.6    1886   728.5 1889.76   738.5 1890.02   770.1 1885.45
   778.4 1885.26   790.1 1886.69   798.4  1888.4  1007.9 1889.17  1357.2 1896.06
  1496.9 1897.35  1576.8 1899.39  1706.5 1904.55  1746.4 1904.21  1796.3  1905.1
#Mann= 3 , 0 , 0
       0     .08       0   770.1    .045       0   790.1     .08       0
Bank Sta=770.1,790.1
XS Rating Curve= 0 ,0
Exp/Cntr=0.3,0.1

Type RM Length L Ch R = 1 ,2508.2  ,651.5,651.9,651.9
XS GIS Cut Line= 3
     1858722.178      281252.579     1859175.298      281458.877
     1860679.338      281583.617
#Sta/Elev= 30
       0  1939.5   139.4 1929.96   179.2 1930.99   209.1 1934.56     239 1933.59
   278.8 1928.86   368.4 1907.07   378.4 1905.64     458 1908.79   507.9 1896.85
   527.9 1894.92   727.8 1892.98   797.7 1890.07   877.7 1888.39  1257.5 1888.88
  1407.4 1884.75  1447.4 1886.32  1487.4 1889.32  1497.4  1888.9  1527.3 1884.03
  1547.3 1882.45  1557.3 1882.26  1577.3 1882.48  1777.2 1889.92  1817.2  1892.7
  1897.1 1900.47  1937.1 1911.06  1957.1 1915.38  1987.1 1920.89  2007.1 1922.22
#Mann= 3 , 0 , 0
       0     .08       0  1547.3    .045       0  1577.3     .08       0
Bank Sta=1547.3,1577.3
XS Rating Curve= 0 ,0
Exp/Cntr=0.3,0.1

Type RM Length L Ch R = 1 ,1856.4  ,526.7,526.9,527.4
XS GIS Cut Line= 3
     1858641.132      282037.249     1860171.226      282188.336
     1860579.288      282222.625
#Sta/Elev= 30
       0 1910.88    39.9 1901.78    49.9    1898   139.8 1892.64   239.6 1894.05
   559.1 1889.57   988.4    1889  1158.1 1887.62    1218 1888.15    1268  1891.4
  1287.9 1891.92  1317.9 1890.47  1347.8 1887.41  1417.7 1883.52  1477.6 1887.08
  1507.6 1887.31  1517.6 1885.97  1537.5 1881.56  1557.5 1880.41  1567.5  1880.9
  1577.5 1882.41  1647.4 1888.77  1697.3 1894.14  1727.3 1900.48  1737.3 1904.59
  1747.3 1906.54  1817.2 1912.15  1847.2 1912.16  1907.1 1906.43    1947 1907.76
#Mann= 3 , 0 , 0
       0      .1       0  1537.5    .045       0  1577.5      .1       0
Bank Sta=1537.5,1577.5
XS Rating Curve= 0 ,0
Exp/Cntr=0.3,0.1

Type RM Length L Ch R = 1 ,1329.5  ,743.6,746.3,748.9
XS GIS Cut Line= 3
     1858873.227      282579.046     1860508.378      282752.763
     1860690.368      282738.976
#Sta/Elev= 30
       0 1912.05    59.8 1894.54    79.7 1887.28    89.7 1886.89     568 1887.91
   647.8 1889.24   727.5 1888.13   916.8 1887.29  1076.3 1884.01    1166 1881.16
  1195.9 1882.17  1205.9 1883.79  1215.8 1884.26  1248.5 1883.44  1268.5 1883.88
  1275.6 1885.31  1285.6 1890.68  1295.6  1892.6  1365.3 1898.92  1474.9 1902.91
  1584.6 1905.12  1604.5 1906.36  1663.6 1913.87  1682.8 1917.48  1740.4 1924.44
    1750 1926.62  1759.6 1930.96  1778.8 1935.77  1788.4  1937.6  1826.9 1941.79
#Mann= 3 , 0 , 0
       0     .08       0  1248.5    .045       0  1268.5     .08       0
#XS Ineff= 2 , 0
          647.89 1889.24
Permanent Ineff=
       F       F
Bank Sta=1248.5,1268.5
XS Rating Curve= 0 ,0
Exp/Cntr=0.3,0.1

Type RM Length L Ch R = 1 ,582.8   ,608.5,582.8,557.1
XS GIS Cut Line= 3
     1858682.046      283053.782     1860472.531      283444.876
      1860513.68      283473.099
#Sta/Elev= 30
       0 1944.63    19.9 1938.78    39.8 1931.83    49.8 1924.54    99.6  1904.2
   119.5  1896.7   129.5 1890.55   139.4 1887.62   149.4 1886.72   268.9 1883.96
   378.5 1882.73   448.2 1882.73   478.1 1883.72     767  1882.7  1095.6 1883.85
  1155.4 1883.52  1235.1 1881.58    1265  1882.2  1314.8 1885.01 1384.21 1886.94
  1424.3 1885.42  1434.3 1884.42  1444.2 1881.82  1448.2  1881.8  1468.2 1882.08
  1523.9 1884.21  1812.8 1889.44  1842.7 1891.95  1852.7 1894.64  1882.6 1899.85
#Mann= 3 , 0 , 0
       0     .08       0  1448.2    .045       0  1468.2     .08       0
#XS Ineff= 2 , 0
         1383.95 1886.91
Permanent Ineff=
       F       F
Bank Sta=1448.2,1468.2
XS Rating Curve= 0 ,0
Exp/Cntr=0.3,0.1

Chan Stop Cuts=-1
Use User Specified Reach Order=0
Composite Channel Slope=5